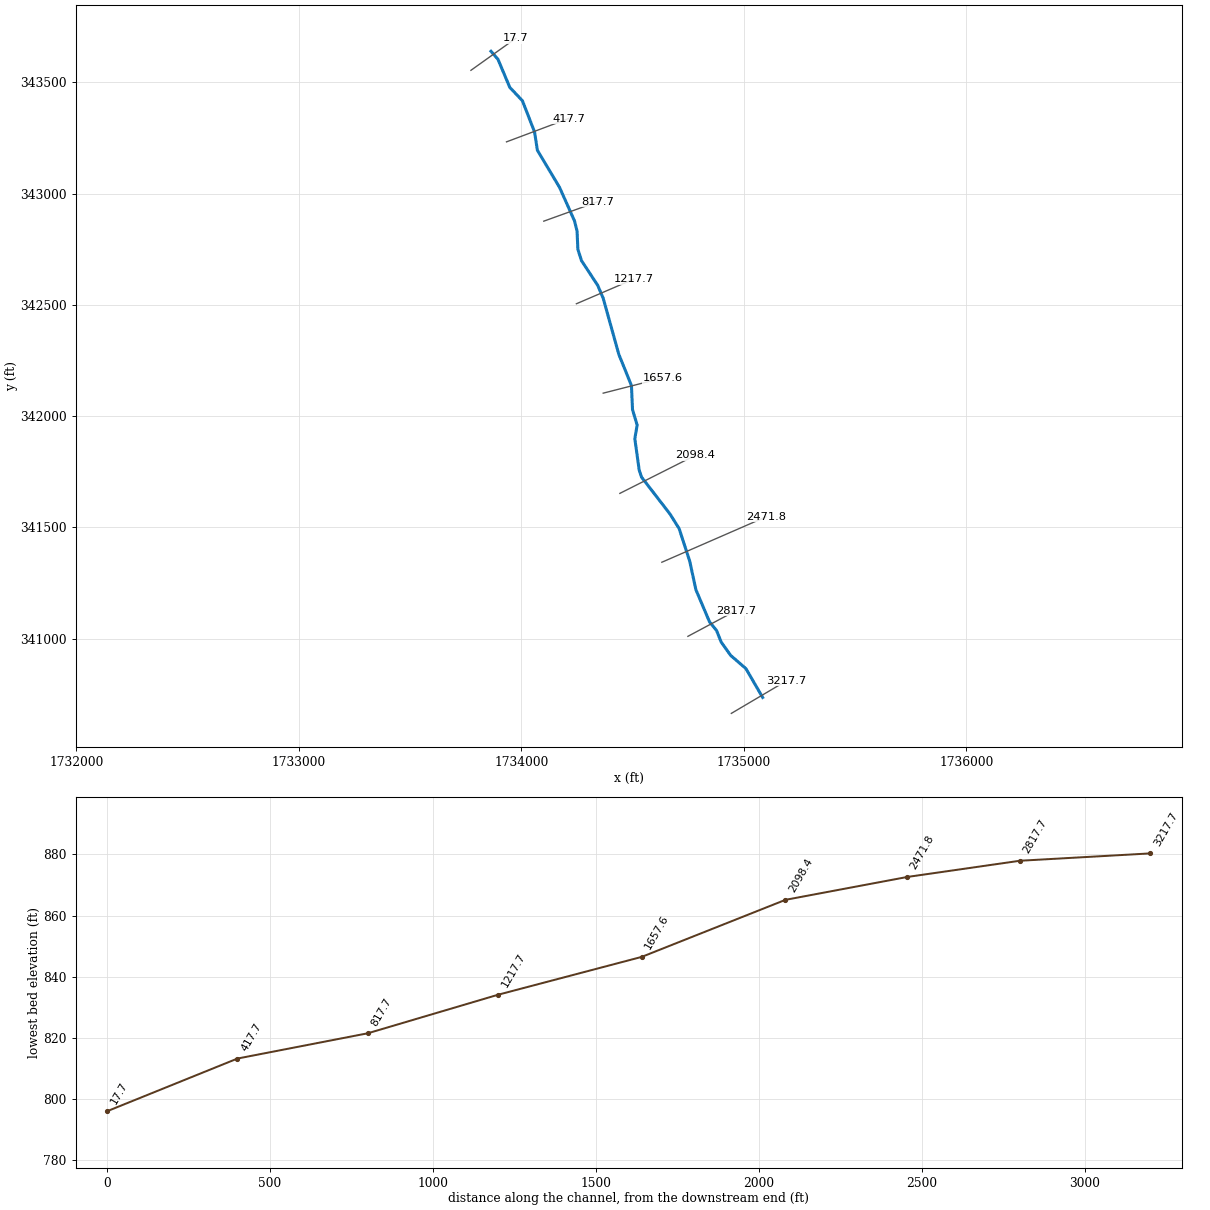
--- BENDBRNCH.prj (project) ---

Proj Title=BENDBRNCH
Current Plan=p01
Default Exp/Contr=0,0
English Units
Geom File=g01
Flow File=f01
Plan File=p01
BEGIN DESCRIPTION:
END DESCRIPTION:
DSS Export Rating Curves= 0
DSS Export Rating Curve Sorted= 0
DSS Export Volume Flow Curves= 0
DXF OffsetX= 0
DXF OffsetY= 0
DXF ScaleX= 0
DXF ScaleY= 0

--- BENDBRNCH.p01 (plan) ---

Plan Title=Floodplain
Program Version=4.00
Geom File=g01
Flow File=f01
K Sum by GR=0
Std Step Tol=0.01
Critical Tol=0.01
Num of Std Step Trials=20
Max Error Tol=0.3
Flow Tol Ratio=0.001
Split Flow NTrial=30
Split Flow Tol=0.02
Split Flow Ratio=0.02
Log Output Level=0
Friction Slope Method=1
Unsteady Friction Slope Method=2
Unsteady Bridges Friction Slope Method=1
Global Log Level=0
CheckData=False
Run HTab=0
Run UNet=0
Run PostProcess=0
UNET Theta=0
UNET Theta Warmup=0
UNET ZTol=0
UNET ZSATol=0
UNET MxIter=0
UNET MaxInSteps=0
UNET DtIC=0
UNET DtMin=0
UNET MaxCRTS=0
UNET WFStab=0
UNET SFStab=0
UNET WFX=0
UNET SFX=0
UNET DSS MLevel=0
UNET DZMax Abort=0
UNET Convert EG Bridges=0
UNET Use Existing IB Tables=0
UNET Froude Limit=0
UNET Froude Power=0
Write IC File=0
Echo Input=False
Echo Output=False
Write Detailed=0

--- BENDBRNCH.f01 (steady flow) ---

Flow Title=NFF Regression Equation
Program Version=4.00
Number of Profiles=1
Profile Names=P100yr
River Rch & RM=BENDBRNCH,Main      ,3217.7
912.4937
River Rch & RM=BENDBRNCH,Main      ,17.7
1004.888
Boundary for River Rch & Prof#=BENDBRNCH,Main      ,1
Up Type=0
Dn Type=3
Dn Slope=0.031726

--- BENDBRNCH.g01 (geometry) ---

Geom Title=USGS 10m DEM
Program Version=4.10

River Reach=BENDBRNCH       ,Main
Reach XY= 30
     1735084.057      340735.621     1735008.774       340865.34
      1734940.44      340924.408     1734897.586      340984.635
     1734876.739      341036.754     1734845.467      341074.975
     1734784.082       341219.75     1734756.286      341348.311
     1734708.799      341494.244     1734668.262      341559.104
     1734539.701      341725.885     1734529.278      341757.156
     1734509.588      341898.457     1734520.012      341959.842
     1734499.164      342029.334     1734494.532      342137.047
      1734437.78       342277.19     1734367.129      342530.836
     1734342.807      342587.588      1734269.84      342698.776
     1734253.626      342749.736     1734250.151      342830.811
     1734238.569      342877.139     1734171.393      343027.705
     1734071.788      343194.486     1734059.047      343276.719
     1734004.612      343416.861      1733947.86      343477.088
     1733894.582      343603.332     1733863.125      343639.447

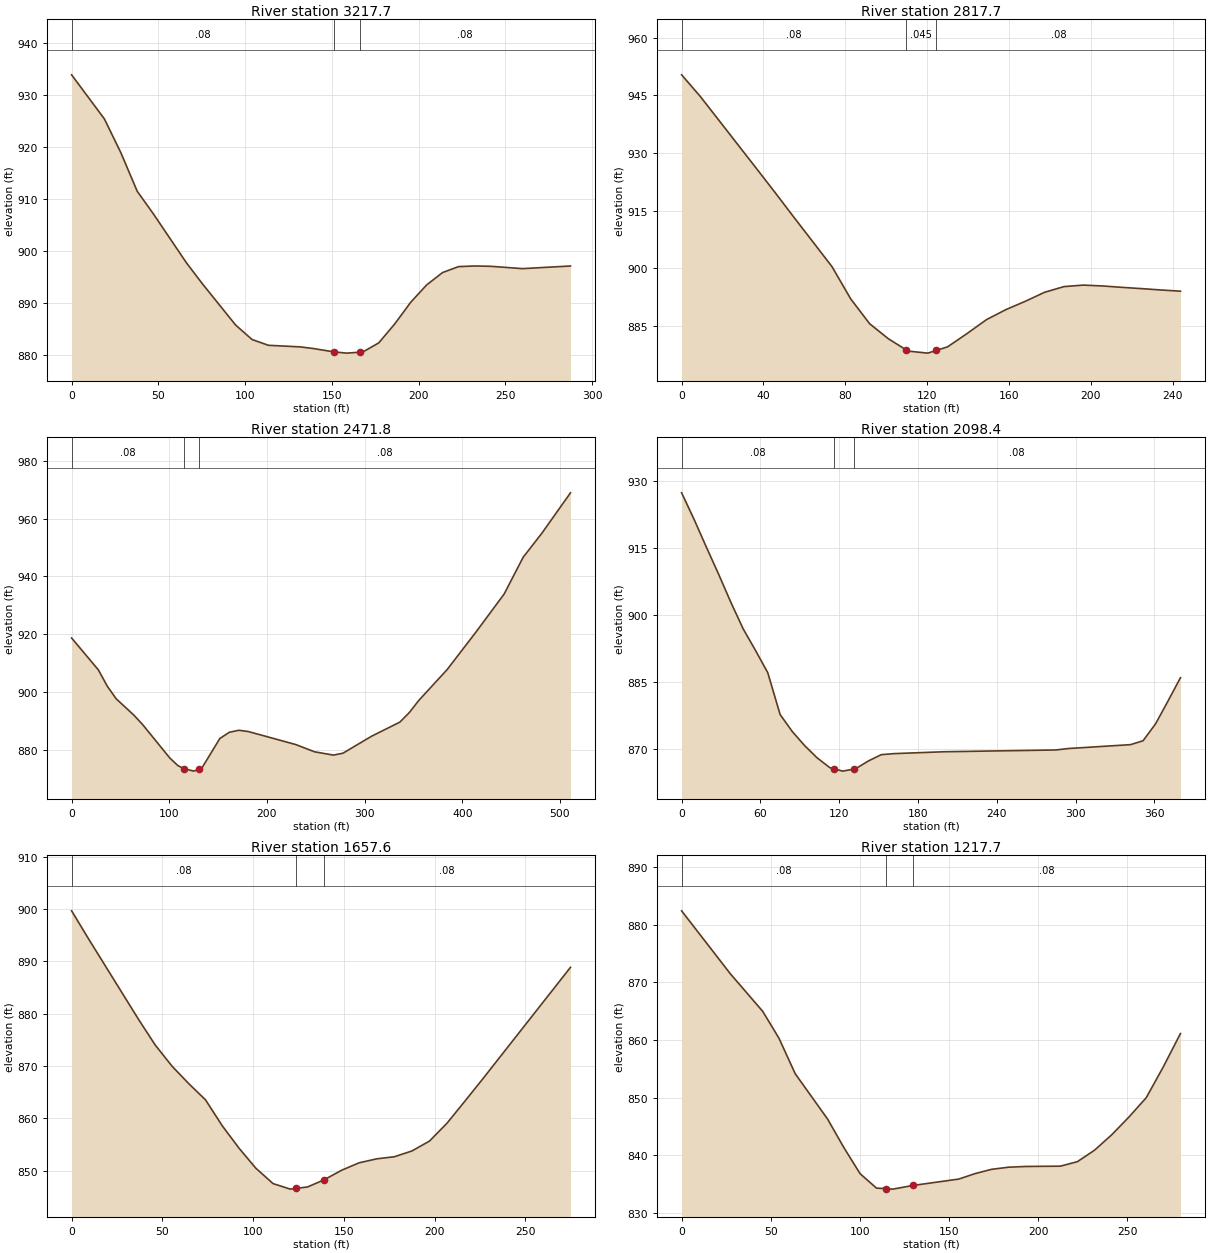
Type RM Length L Ch R = 1 ,3217.7  ,401,400,399
XS GIS Cut Line= 6
      1734943.32      340664.104     1735049.147      340726.551
       1735056.8      340731.067     1735063.355      340734.935
     1735079.859      340744.674     1735190.963      340810.235
#Sta/Elev= 26
       0  933.89    18.9   925.4    28.4  918.88    37.8  911.48    47.3  907.03
    66.2  897.68    75.6  893.56    94.5  885.72     104  882.92   113.4  881.81
   131.8   881.5   139.4  881.18   151.2  880.54   158.5   880.3   166.2  880.48
   167.8  880.51     177  882.27   186.2  885.91   195.4  890.08   204.6  893.43
   213.8  895.82     223  896.96   232.2  897.08   241.5  897.02   259.9  896.57
   287.5  897.08
#Mann= 3 , 0 , 0
       0     .08       0   151.2    .045       0   166.2     .08       0
Bank Sta=151.2,166.2
XS Rating Curve= 0 ,0
Exp/Cntr=0.3,0.1

Type RM Length L Ch R = 1 ,2817.7  ,347.6,345.8,344.1
XS GIS Cut Line= 4
      1734748.14      341010.293     1734837.299      341057.949
     1734871.231      341076.086     1734963.105      341125.195
#Sta/Elev= 29
       0  950.35     9.2  944.68    18.4   938.4    27.6   932.1    36.8  925.82
      46  919.49    55.1  913.12    64.3  906.78    73.5  900.41    82.7  891.98
    91.9  885.55   101.1  881.62   109.5  878.83   110.7  878.43   120.3   877.9
   124.5  878.61     130  879.54   139.6  883.03     149  886.62   158.5  889.23
     168   891.4   177.4  893.74   186.9  895.22   196.4  895.61   205.9  895.38
   215.3  895.02   224.8  894.69   234.3  894.34   243.8  894.02
#Mann= 3 , 0 , 0
       0     .08       0   109.5    .045       0   124.5     .08       0
Bank Sta=109.5,124.5
XS Rating Curve= 0 ,0
Exp/Cntr=0.3,0.1

Type RM Length L Ch R = 1 ,2471.8  ,372.3,373.4,374.6
XS GIS Cut Line= 4
     1734631.076      341343.263     1734723.106      341383.369
     1734761.324      341400.024     1735099.323      341547.324
#Sta/Elev= 30
       0  918.67    27.4  907.64    36.5  902.02    45.6  897.65    63.9  891.93
      73   888.6   100.4   877.2   108.7  874.54   115.1  873.42   125.4   872.6
   130.1  873.31   133.7  873.85   151.8   883.9   161.5  886.04   171.2  886.74
   180.9   886.3   229.4  881.81   248.8  879.28   268.2  878.14   277.9  878.81
     307  884.65   336.1  889.56   345.8  892.87   355.5  897.06   384.6  907.77
   413.8  920.62   442.9  933.89   462.3  946.57   481.7  955.01   510.8   968.9
#Mann= 3 , 0 , 0
       0     .08       0   115.1    .045       0   130.1     .08       0
Bank Sta=115.1,130.1
XS Rating Curve= 0 ,0
Exp/Cntr=0.3,0.1

Type RM Length L Ch R = 1 ,2098.4  ,445.8,440.8,435.8
XS GIS Cut Line= 4
     1734442.411      341652.715     1734534.468      341699.095
     1734578.169      341721.111     1734781.576       341823.59
#Sta/Elev= 28
       0  927.35     9.4  921.48    18.7  915.31    28.1  909.21    37.5  902.87
    46.9  896.92    56.2  892.15    65.6  887.14      75  877.79    84.3  873.97
    93.7  870.83   103.1  868.12   112.9   865.9   116.3  865.63   122.6  865.13
   131.3  865.59   132.4  865.65   142.2   867.4     152  868.81   161.5  869.04
   199.5  869.46   284.9  869.86   294.4  870.18   341.8  871.05   351.3  871.92
   360.8  875.68   370.3  880.79   379.8  886.02
#Mann= 3 , 0 , 0
       0     .08       0   116.3    .045       0   131.3     .08       0
Bank Sta=116.3,131.3
XS Rating Curve= 0 ,0
Exp/Cntr=0.3,0.1

Type RM Length L Ch R = 1 ,1657.6  ,436.4,439.9,443.4
XS GIS Cut Line= 4
     1734367.487      342103.039     1734465.826      342128.179
      1734520.95      342142.271     1734633.807      342171.123
#Sta/Elev= 25
       0  899.63     9.2  894.36    36.9   878.9    46.1     874    55.4  869.95
    64.6  866.62    73.8  863.54      83   858.6    92.3   854.3   101.5   850.5
     111  847.56   120.5   846.5   123.9  846.65     130  846.91   138.9  848.24
   148.9  850.12   158.4  851.52   168.1  852.28   177.8  852.68   187.5  853.78
   197.2  855.67   206.9   859.1   216.6  863.24   226.4  867.47   274.9  888.84
#Mann= 3 , 0 , 0
       0     .08       0   123.9    .045       0   138.9     .08       0
Bank Sta=123.9,138.9
XS Rating Curve= 0 ,0
Exp/Cntr=0.3,0.1

Type RM Length L Ch R = 1 ,1217.7  ,401.4,400,398.6
XS GIS Cut Line= 4
     1734247.041      342504.724     1734338.967       342544.24
     1734406.702      342573.356     1734504.127      342615.235
#Sta/Elev= 25
       0  882.41    27.3  871.51    45.5  864.98    54.6  860.33    63.7  854.18
    81.9   846.3      91  841.37   100.1  836.84   109.3  834.34   114.6  834.24
   118.5  834.16   129.6  834.79   155.4   835.9   164.6  836.85   173.8  837.59
   183.4  837.96   193.1  838.09   212.4  838.14     222  838.92   231.6  840.91
   241.3   843.6   250.9  846.66   260.6  850.01   270.2  855.37   279.8  861.14
#Mann= 3 , 0 , 0
       0     .08       0   114.6    .045       0   129.6     .08       0
Bank Sta=114.6,129.6
XS Rating Curve= 0 ,0
Exp/Cntr=0.3,0.1

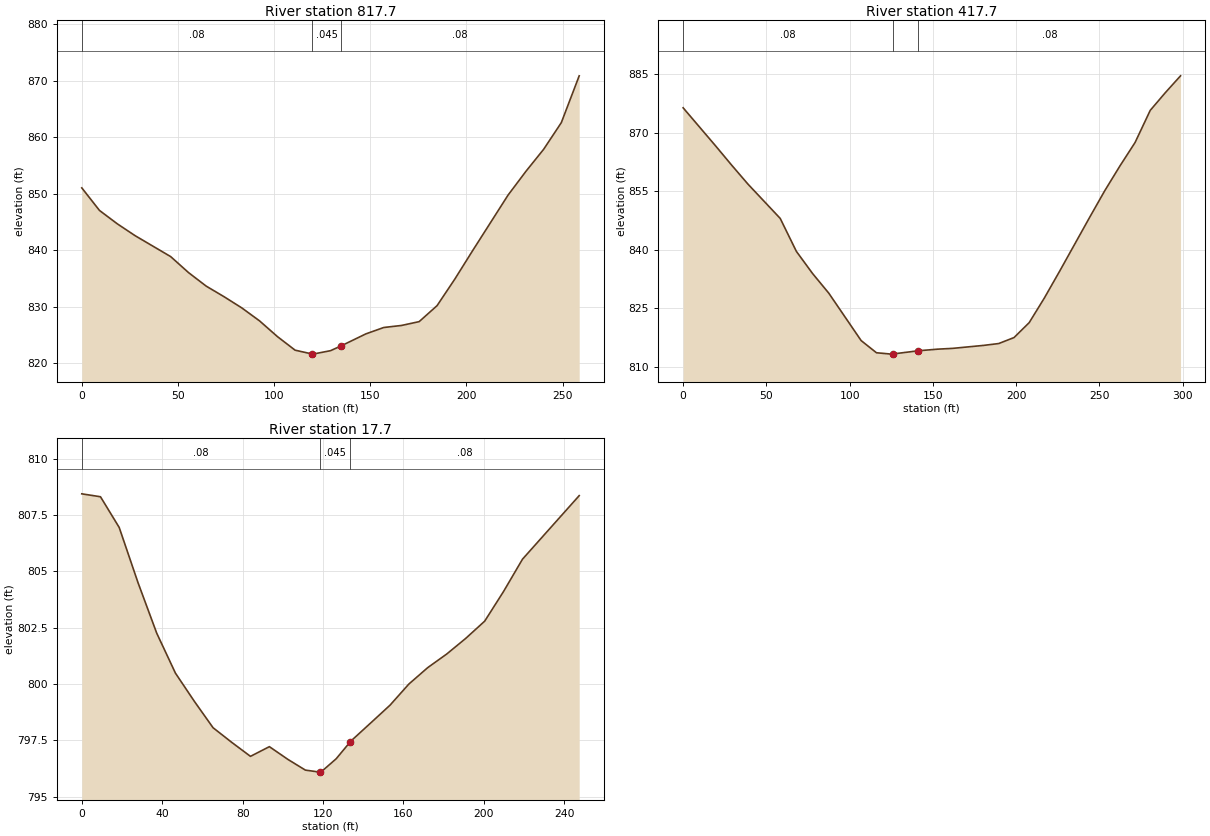
Type RM Length L Ch R = 1 ,817.7   ,399.7,400,400.3
XS GIS Cut Line= 4
     1734100.487       342875.92     1734196.136      342910.401
     1734239.451      342926.015     1734343.735      342963.608
#Sta/Elev= 28
       0  851.03     9.2  847.03    18.5  844.65    27.7  842.56    46.2  838.85
    55.5  836.01    64.7  833.61      74  831.73    83.2  829.75    92.4  827.46
   101.7  824.67   110.9  822.26   119.7  821.59   120.1  821.56   129.3  822.17
   134.7     823   147.7  825.15     157  826.28   166.2  826.64   175.4  827.32
   184.7  830.15   193.9  834.84   203.1  839.85   221.6  849.74   230.9  853.96
   240.1  857.86   249.3  862.59   258.6  870.89
#Mann= 3 , 0 , 0
       0     .08       0   119.7    .045       0   134.7     .08       0
Bank Sta=119.7,134.7
XS Rating Curve= 0 ,0
Exp/Cntr=0.3,0.1

Type RM Length L Ch R = 1 ,417.7   ,394,400,406
XS GIS Cut Line= 4
     1733932.953      343232.295     1734033.032      343269.864
     1734118.935      343302.111      1734212.62      343337.279
#Sta/Elev= 28
       0  876.41    19.4   866.7    29.2  861.69    38.9  856.87    58.3  848.07
      68  839.63    77.7  833.97    87.5   828.9   106.9  816.77   116.1  813.65
   125.2   813.3   126.3  813.36   141.3  814.16   152.8  814.57     162  814.78
   180.3  815.53   189.5  816.01   198.7  817.54   207.8  821.36   216.8  827.59
     226  834.47   244.1  848.33   253.2  855.17   262.3  861.51   271.4  867.52
   280.5  875.75   289.6   880.3   298.7   884.6
#Mann= 3 , 0 , 0
       0     .08       0   126.3    .045       0   141.3     .08       0
Bank Sta=126.3,141.3
XS Rating Curve= 0 ,0
Exp/Cntr=0.3,0.1

Type RM Length L Ch R = 1 ,17.7    ,14,17.7,21.4
XS GIS Cut Line= 6
     1733773.151      343553.783     1733856.657      343613.385
     1733863.698      343618.411     1733882.288       343631.68
      1733890.23      343637.348     1733974.547      343697.529
#Sta/Elev= 30
       0  808.44     9.3  808.31    18.6  806.95      28  804.49    37.3  802.25
    46.6  800.48      56  799.23    65.3  798.06    74.6  797.41    83.9  796.79
    93.3  797.22   102.6  796.65   111.2  796.18   118.4  796.09   118.9  796.09
   126.5  796.68   133.4  797.42   134.1  797.49   143.8  798.28   153.3  799.06
   162.7     800   172.1  800.73   181.5  801.33   190.9  802.02   200.4  802.79
   209.8  804.11   219.2  805.54   228.6  806.48     238  807.42   247.4  808.36
#Mann= 3 , 0 , 0
       0     .08       0   118.4    .045       0   133.4     .08       0
Bank Sta=118.4,133.4
XS Rating Curve= 0 ,0
Exp/Cntr=0.3,0.1

Chan Stop Cuts=-1
Use User Specified Reach Order=0
Composite Channel Slope=5